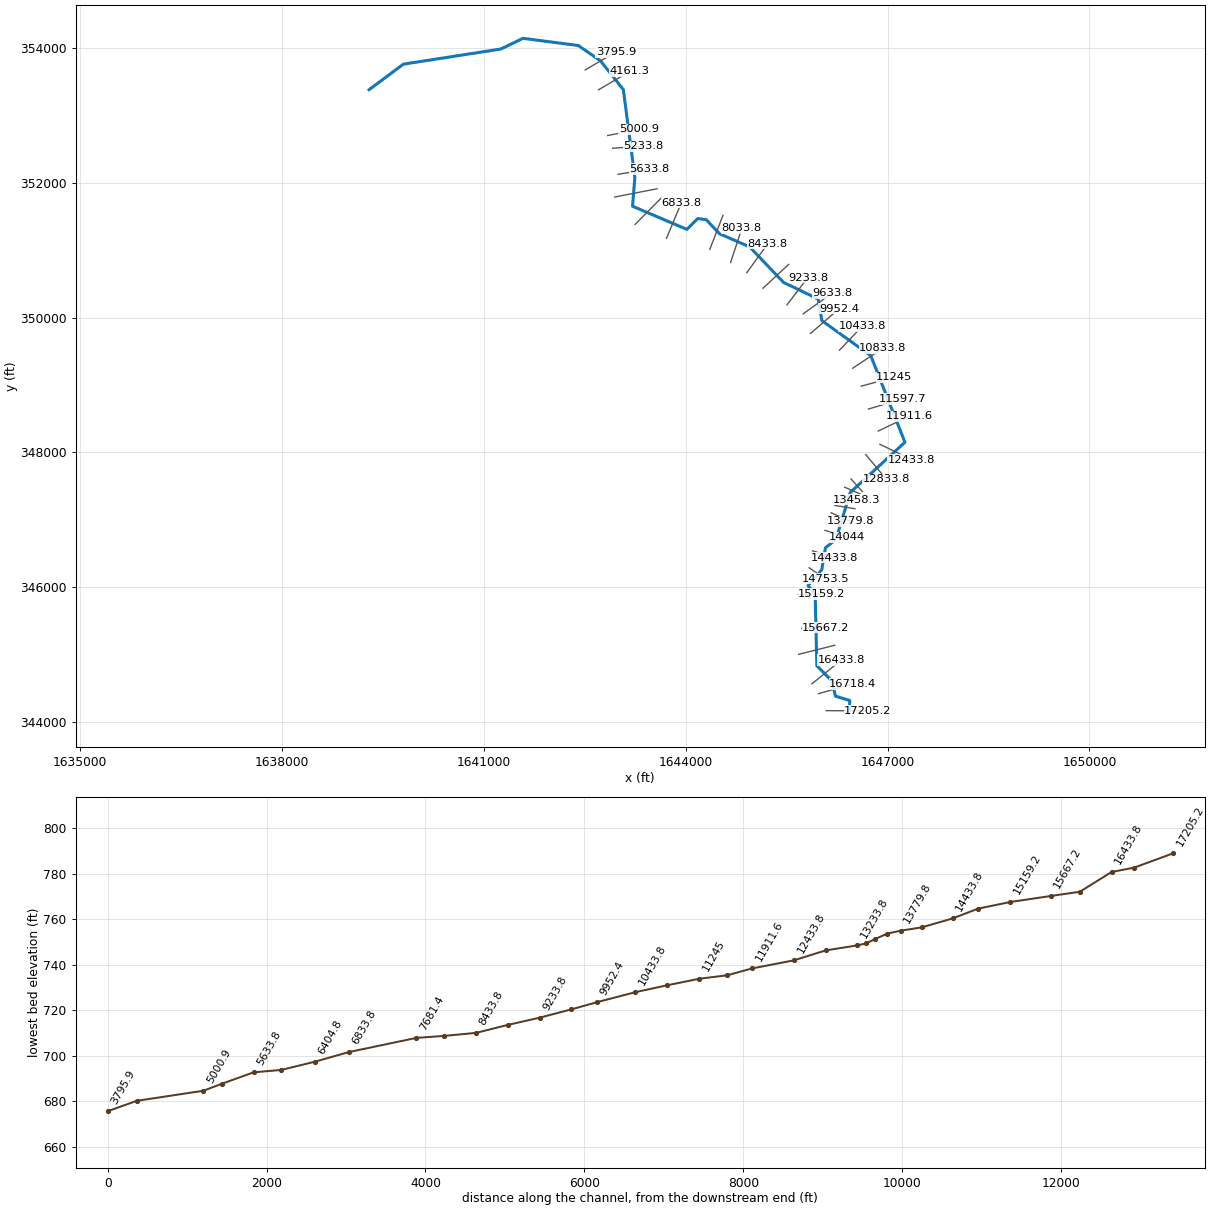
--- BUCKFRK.prj (project) ---

Proj Title=BUCKFRK
Current Plan=p01
Default Exp/Contr=0,0
English Units
Geom File=g01
Flow File=f01
Plan File=p01
BEGIN DESCRIPTION:
END DESCRIPTION:
DSS Export Rating Curves= 0
DSS Export Rating Curve Sorted= 0
DSS Export Volume Flow Curves= 0
DXF OffsetX= 0
DXF OffsetY= 0
DXF ScaleX= 0
DXF ScaleY= 0

--- BUCKFRK.p01 (plan) ---

Plan Title=Floodplain
Program Version=4.00
Geom File=g01
Flow File=f01
K Sum by GR=0
Std Step Tol=0.01
Critical Tol=0.01
Num of Std Step Trials=20
Max Error Tol=0.3
Flow Tol Ratio=0.001
Split Flow NTrial=30
Split Flow Tol=0.02
Split Flow Ratio=0.02
Log Output Level=0
Friction Slope Method=1
Unsteady Friction Slope Method=2
Unsteady Bridges Friction Slope Method=1
Global Log Level=0
CheckData=False
Run HTab=0
Run UNet=0
Run PostProcess=0
UNET Theta=0
UNET Theta Warmup=0
UNET ZTol=0
UNET ZSATol=0
UNET MxIter=0
UNET MaxInSteps=0
UNET DtIC=0
UNET DtMin=0
UNET MaxCRTS=0
UNET WFStab=0
UNET SFStab=0
UNET WFX=0
UNET SFX=0
UNET DSS MLevel=0
UNET DZMax Abort=0
UNET Convert EG Bridges=0
UNET Use Existing IB Tables=0
UNET Froude Limit=0
UNET Froude Power=0
Write IC File=0
Echo Input=False
Echo Output=False
Write Detailed=0

--- BUCKFRK.f01 (steady flow) ---

Flow Title=NFF Regression Equation
Program Version=4.00
Number of Profiles=1
Profile Names=P100yr
River Rch & RM=BUCKFRK,Main      ,17205.2
855.4418
River Rch & RM=BUCKFRK,Main      ,16718.4
912.4937
River Rch & RM=BUCKFRK,Main      ,15667.2
1007.708
River Rch & RM=BUCKFRK,Main      ,14044
1055.084
River Rch & RM=BUCKFRK,Main      ,11911.6
1165.353
River Rch & RM=BUCKFRK,Main      ,8033.8
1248.013
River Rch & RM=BUCKFRK,Main      ,5982.1
1386.668
Boundary for River Rch & Prof#=BUCKFRK,Main      ,1
Up Type=0
Dn Type=3
Dn Slope=0.003235

--- BUCKFRK.g01 (geometry) ---

Geom Title=USGS 10m DEM
Program Version=4.10

River Reach=BUCKFRK         ,Main
Reach XY= 30
     1646431.468      344123.035     1646439.577      344314.179
      1646227.58      344377.894       1646168.5      344609.584
     1645949.552      344830.848     1645925.225      345888.513
     1645818.648      346019.418     1646022.535      346254.583
     1646076.982      346581.265     1646234.531      346707.537
     1646445.369      347402.607     1647258.601      348148.648
       1646751.2      349434.527     1646024.852      349954.671
     1645969.246      350275.562     1645453.736      350523.471
     1644950.968      351050.565     1644503.807      351245.185
      1644306.87      351453.706     1644179.441      351471.082
     1644018.417      351310.058     1643210.977      351654.118
      1643245.73      352081.586      1643074.28         353386.
     1642733.696      353814.626     1642404.696      354040.524
     1641583.355      354147.102     1641254.355      353988.394
     1639806.293      353763.655     1639295.928      353384.457

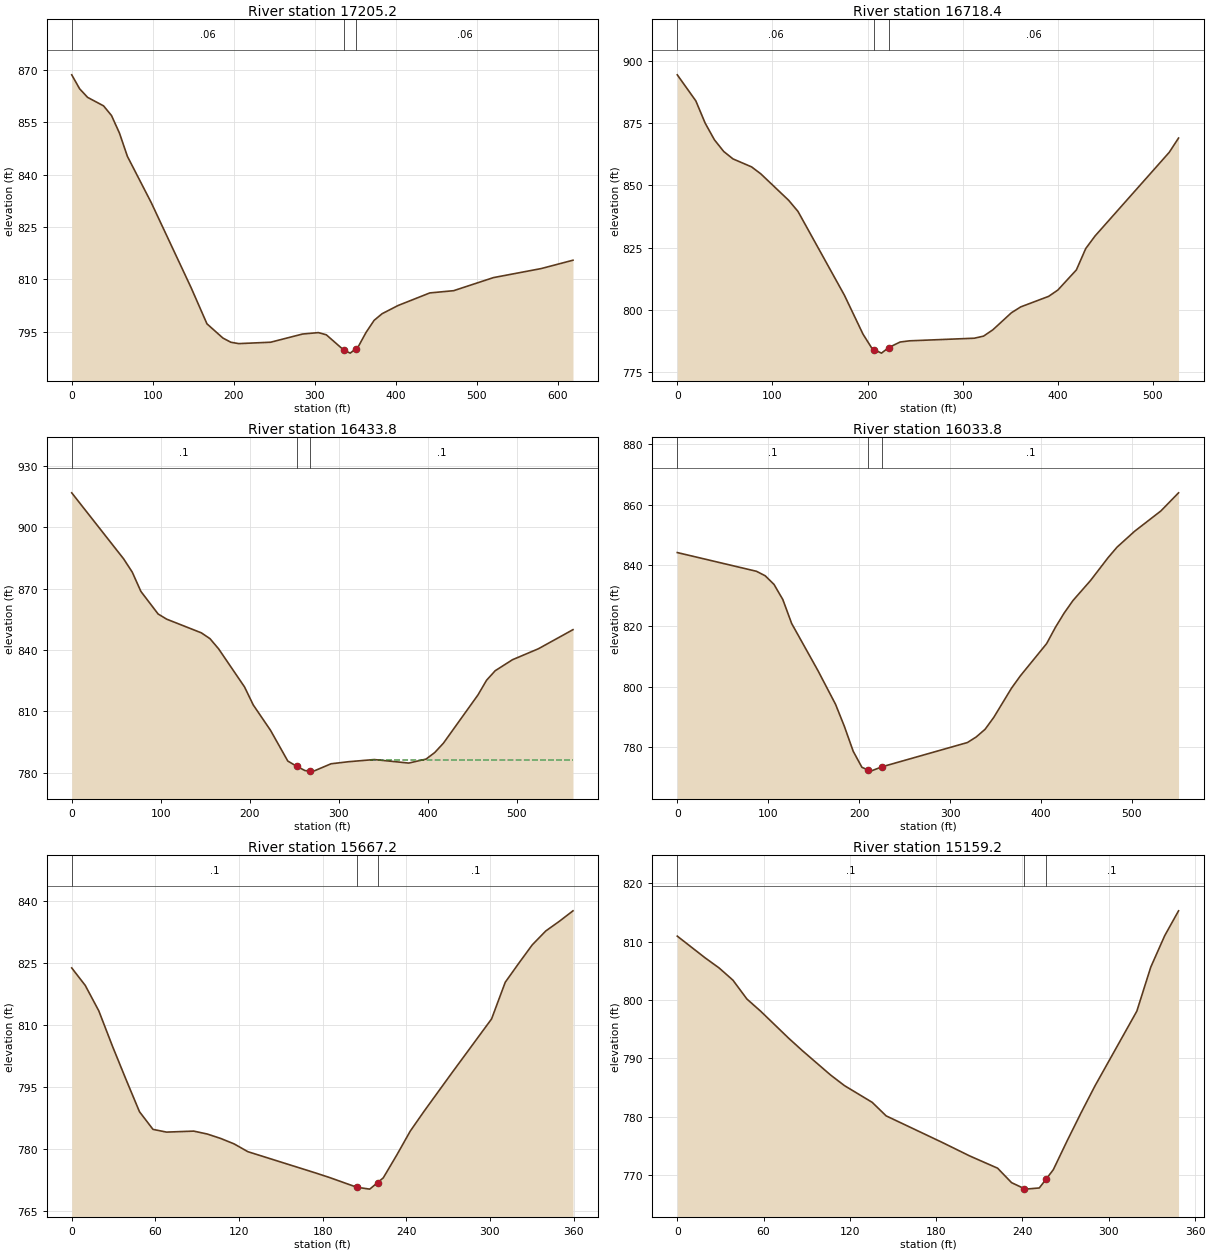
Type RM Length L Ch R = 1 ,17205.2 ,488.3,486.7,495
XS GIS Cut Line= 2
      1646088.51      344163.487     1646707.138      344160.093
#Sta/Elev= 30
       0  868.53     9.8  864.52    19.6  862.08    39.3  859.65    49.1  856.88
    58.9  851.87    68.7  845.21    98.2  831.94   147.3  807.66   166.9   797.3
   186.6  793.23   196.4  792.03   206.2  791.64   245.5  792.04   284.8  794.38
   304.4  794.79   314.2  794.16   335.9  789.76   343.7  788.92   350.9  790.24
   353.5  790.72   363.3  794.87   373.2   798.3     383  800.19   402.6  802.53
   441.9  806.14   471.3  806.78   520.4  810.52   579.4  813.11   618.6   815.5
#Mann= 3 , 0 , 0
       0     .06       0   335.9    .045       0   350.9     .06       0
Bank Sta=335.9,350.9
XS Rating Curve= 0 ,0
Exp/Cntr=0.3,0.1

Type RM Length L Ch R = 1 ,16718.4 ,275.4,284.6,293.7
XS GIS Cut Line= 2
     1645975.572      344415.869      1646482.76      344558.986
#Sta/Elev= 30
       0  894.27    19.5  883.82    29.3  874.91      39  868.24    48.8  863.54
    58.6  860.55    78.1  857.36    87.8  854.57   117.1  843.96   126.9   839.5
   175.7  805.91   195.2  790.34   204.9  784.45   207.2  784.04   214.7  782.69
   222.2  784.91   234.2  787.13     244  787.62   312.3  788.67     322  789.51
   331.8  792.05   351.3  798.88   361.1  801.23   390.4  805.45   400.1  807.98
   419.6  816.06   429.4   824.6   439.2  829.65   517.2  863.19     527  868.92
#Mann= 3 , 0 , 0
       0     .06       0   207.2    .045       0   222.2     .06       0
Bank Sta=207.2,222.2
XS Rating Curve= 0 ,0
Exp/Cntr=0.3,0.1

Type RM Length L Ch R = 1 ,16433.8 ,409.8,399.9,390
XS GIS Cut Line= 2
     1645876.622      344562.314      1646315.25      344915.753
#Sta/Elev= 30
       0  916.88    58.3   884.6      68  878.12    77.7  868.68    97.1  857.61
   106.8  855.07   145.7  848.39   155.4  845.54   165.1  840.55   194.2  821.94
     204  813.13   223.4  800.72   242.8   785.7   252.8  783.12   262.2  781.02
   267.8  780.87   271.9  780.76   291.4  784.35   310.8  785.35   339.9  786.42
   378.8   784.7   398.2  786.65   407.9  789.83   417.6  794.37   456.5  818.01
   466.2  825.22   475.9  829.87   495.3  835.25   524.5  840.62   563.3  849.95
#Mann= 3 , 0 , 0
       0      .1       0   252.8    .045       0   267.8      .1       0
#XS Ineff= 2 , 0
                           335.4          786.41
Permanent Ineff=
       F       F
Bank Sta=252.8,267.8
XS Rating Curve= 0 ,0
Exp/Cntr=0.3,0.1

Type RM Length L Ch R = 1 ,16033.8 ,371.5,366.4,361.3
XS GIS Cut Line= 2
     1645679.386      344999.844     1646214.308      345133.575
#Sta/Elev= 30
       0   844.2    87.1  838.02    96.7  836.54   106.4  833.69   116.1  828.69
   125.8   820.8   154.8  805.21   174.1  794.12   183.8  786.85   193.5  778.64
   203.1  773.34   210.2  772.42   212.8  772.08   225.2  773.51   319.2  781.52
   328.9  783.37   338.6  785.89   348.2  789.84   367.6  799.43   377.3  803.48
   406.3  814.16     416  819.55   425.6  824.25   435.3  828.38   454.6  834.98
     474  842.56   483.7  845.97     503  851.21     532  857.94   551.4  863.91
#Mann= 3 , 0 , 0
       0      .1       0   210.2    .045       0   225.2      .1       0
Bank Sta=210.2,225.2
XS Rating Curve= 0 ,0
Exp/Cntr=0.3,0.1

Type RM Length L Ch R = 1 ,15667.2 ,508.2,508,507.7
XS GIS Cut Line= 2
       1645725.1      345384.325     1646084.455      345396.089
#Sta/Elev= 30
       0  823.75     9.7  819.52    19.4  813.38    29.2  804.83    38.9   796.8
    48.6  788.96    58.3  784.68      68  784.02    87.5  784.26    97.2  783.56
   106.9  782.48   116.6  781.15   126.3  779.29   174.9  774.14   184.6  773.07
   204.5  770.68   213.8  770.22   219.5  771.82   223.5  772.95   233.2  778.48
   242.9  784.28   252.6  788.98   272.1  798.06   301.2  811.41     311  820.28
   320.7  824.87   330.4  829.34   340.1   832.7   349.8  835.03   359.6  837.57
#Mann= 3 , 0 , 0
       0      .1       0   204.5    .045       0   219.5      .1       0
Bank Sta=204.5,219.5
XS Rating Curve= 0 ,0
Exp/Cntr=0.3,0.1

Type RM Length L Ch R = 1 ,15159.2 ,419.2,405.5,391.7
XS GIS Cut Line= 2
     1645674.871      345886.661     1646023.288      345896.057
#Sta/Elev= 28
       0  810.96    19.4  807.23      29  805.52    38.7  803.41    48.4  800.18
    58.1  798.06    77.4  793.47    87.1   791.3   106.5  787.17   116.2  785.34
   135.5  782.47   145.2  780.15     184  775.62   203.3  773.28   222.7  771.18
   232.4   768.7   241.3  767.67     242  767.59   251.7  767.79   256.3  769.27
   261.4  770.91   271.1   775.9   280.8  780.71   290.4  785.29   319.5   798.1
   329.2  805.66   338.9  811.05   348.5   815.3
#Mann= 3 , 0 , 0
       0      .1       0   241.3    .045       0   256.3      .1       0
Bank Sta=241.3,256.3
XS Rating Curve= 0 ,0
Exp/Cntr=0.3,0.1

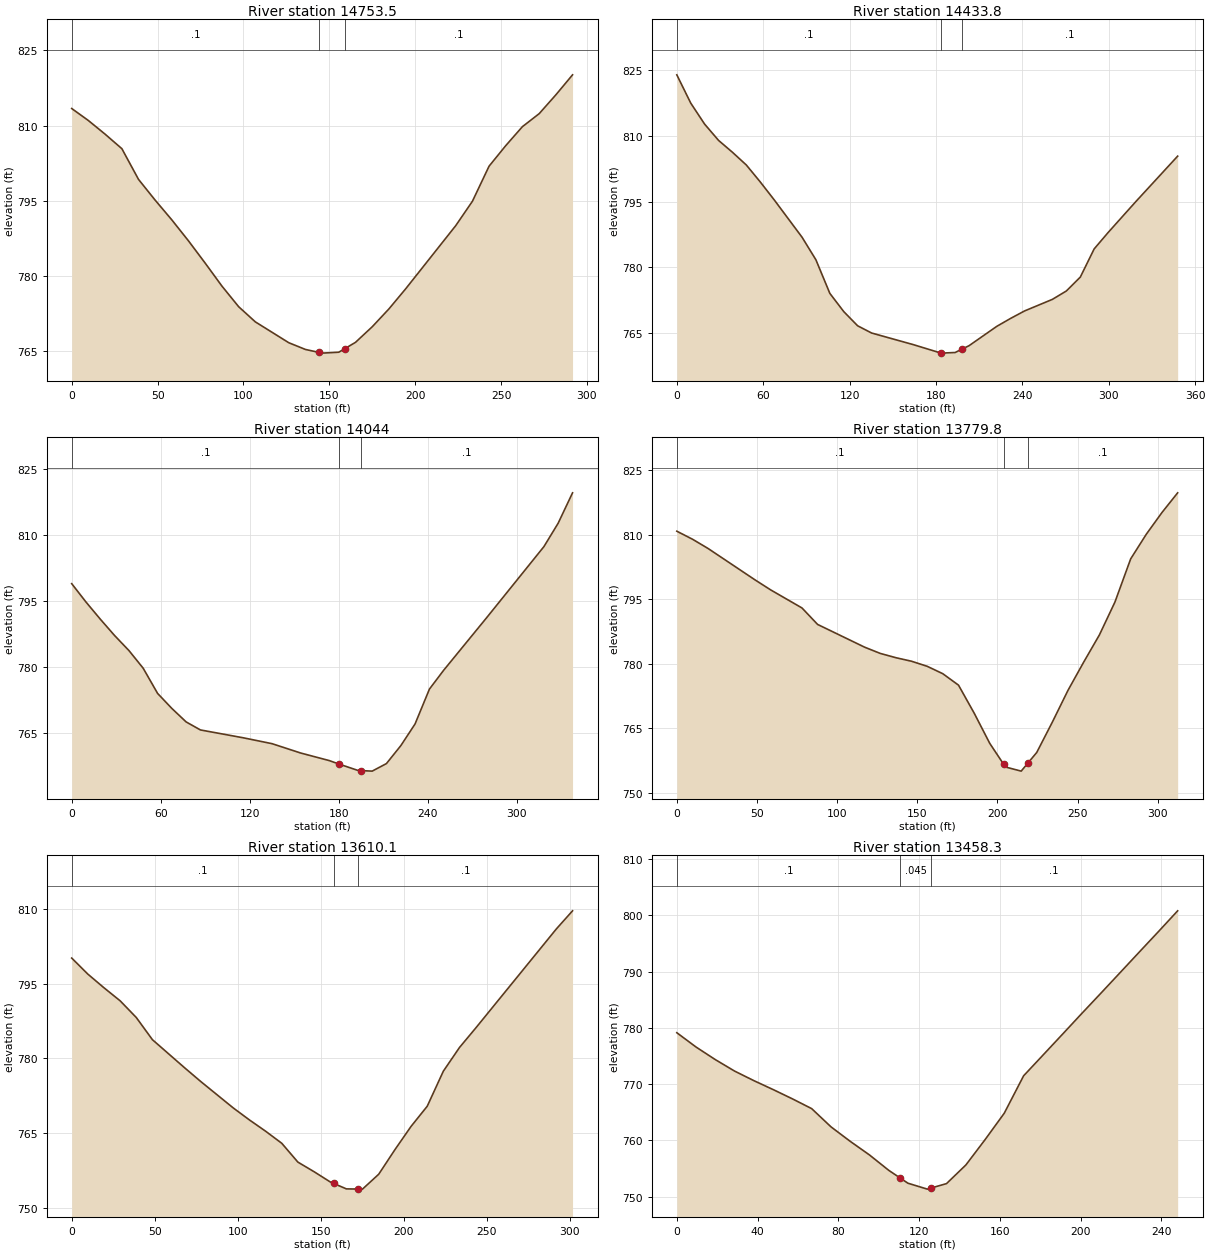
Type RM Length L Ch R = 1 ,14753.5 ,312.2,319.8,327.4
XS GIS Cut Line= 2
     1645834.429       346285.67     1646076.435      346122.978
#Sta/Elev= 30
       0   813.4     9.7  811.01    19.4   808.3    29.2   805.4    38.9  799.28
    48.6  795.14    58.3  791.21      68  787.03    77.8  782.56    87.5  778.01
    97.2  773.92   106.9   770.9   126.4  766.74   136.1   765.4     144  764.81
   145.8  764.67   155.5  764.85     159  765.56   165.2  766.81     175  769.93
   184.7  773.48   194.4  777.46   223.6  790.07   233.3  794.92     243  801.91
   252.7     806   262.4  809.78   272.2  812.38   281.9  816.13   291.6  820.11
#Mann= 3 , 0 , 0
       0      .1       0     144    .045       0     159      .1       0
Bank Sta=144,159
XS Rating Curve= 0 ,0
Exp/Cntr=0.3,0.1

Type RM Length L Ch R = 1 ,14433.8 ,389.6,389.5,389.5
XS GIS Cut Line= 2
     1645886.335      346536.467     1646218.736      346433.694
#Sta/Elev= 30
       0     824     9.7  817.52    19.3  812.74      29  809.01    38.7  806.28
    48.3  803.38      58   799.5    67.6  795.44      87  786.87    96.6  781.73
   106.3  774.04     116  769.86   125.6  766.63   135.3  764.98   164.3  762.32
   183.2  760.42   183.6  760.38   193.3  760.52   198.2  761.31     203  762.08
   222.3  766.51     232  768.34   241.6  770.03   260.9  772.67   270.6  774.59
   280.3  777.77   289.9   784.2   299.6  787.95   318.9  795.04   347.9  805.41
#Mann= 3 , 0 , 0
       0      .1       0   183.2    .045       0   198.2      .1       0
Bank Sta=183.2,198.2
XS Rating Curve= 0 ,0
Exp/Cntr=0.3,0.1

Type RM Length L Ch R = 1 ,14044   ,266.6,264.3,262.1
XS GIS Cut Line= 2
     1646071.199      346840.903     1646392.745      346737.826
#Sta/Elev= 27
       0     799     9.6  794.84    19.3  790.93    28.9  787.23    38.6  783.81
    48.2   779.8    57.9  774.09    67.5  770.68    77.2   767.6    86.8  765.79
   115.8     764   135.1  762.67   154.4  760.55   173.7  758.83   180.1  758.06
     193   756.6   195.1  756.56   202.6  756.44   212.2  758.15   221.9  762.22
   231.5  767.14   241.2  775.06   250.8  779.34   279.8  791.28   318.4  807.41
     328  812.72   337.7  819.62
#Mann= 3 , 0 , 0
       0      .1       0   180.1    .045       0   195.1      .1       0
Bank Sta=180.1,195.1
XS Rating Curve= 0 ,0
Exp/Cntr=0.3,0.1

Type RM Length L Ch R = 1 ,13779.8 ,163.9,169.6,175.3
XS GIS Cut Line= 2
     1646161.984      347101.886      1646448.31      346977.045
#Sta/Elev= 30
       0  810.83     9.8  808.96    19.5  806.81    48.8   799.5    58.6  797.16
    78.1  792.96    87.8  789.14   117.1  783.85   126.9  782.39   136.7  781.39
   146.4  780.57   156.2  779.39   165.9  777.67   175.7  775.01   185.5  768.48
   195.2  761.46   203.8  756.63     205  755.96   214.8     755   218.8  756.79
   224.5  759.34   234.3  766.45     244   773.8   253.8  780.37   263.6   786.7
   273.3  794.36   283.1  804.39   292.8   810.1   302.6  815.17   312.4  819.76
#Mann= 3 , 0 , 0
       0      .1       0   203.8    .045       0   218.8      .1       0
Bank Sta=203.8,218.8
XS Rating Curve= 0 ,0
Exp/Cntr=0.3,0.1

Type RM Length L Ch R = 1 ,13610.1 ,154.2,151.8,149.4
XS GIS Cut Line= 2
     1646216.966      347210.919     1646514.651      347162.247
#Sta/Elev= 28
       0  800.14     9.7  796.92    19.5  794.15    29.2  791.54    38.9  788.19
    48.6  783.74    68.1  778.06    77.8  775.31    97.3  770.02     107  767.62
   116.8  765.34   126.5  762.92   136.2  759.14     146   757.2   155.7  755.15
   157.7  754.86   165.4  753.76   172.7  753.72   175.1  753.71   184.9  756.71
   194.6  761.62   204.3  766.29   214.1  770.37   223.8  777.41   233.5  782.16
   243.3  786.08   291.9  806.01   301.6  809.63
#Mann= 3 , 0 , 0
       0      .1       0   157.7    .045       0   172.7      .1       0
Bank Sta=157.7,172.7
XS Rating Curve= 0 ,0
Exp/Cntr=0.3,0.1

Type RM Length L Ch R = 1 ,13458.3 ,122.2,119,115.8
XS GIS Cut Line= 2
     1646294.454      347364.582     1646533.624      347298.502
#Sta/Elev= 29
       0  779.15     9.5  776.61    19.1  774.36    28.6  772.33    38.2  770.62
    47.7  769.04    57.3  767.38    66.8  765.65    76.4   762.4    85.9  759.83
    95.4  757.42     105  754.67   110.8  753.27   114.5  752.38   124.1  751.33
   125.8  751.51   133.6  752.31   143.2  755.63   152.7  760.13   162.2  764.83
   171.8  771.49   181.3  775.13   190.9  778.82   200.4  782.49     210  786.15
   219.5   789.8     229  793.46   238.6  797.14   248.1  800.83
#Mann= 3 , 0 , 0
       0      .1       0   110.8    .045       0   125.8      .1       0
Bank Sta=110.8,125.8
XS Rating Curve= 0 ,0
Exp/Cntr=0.3,0.1

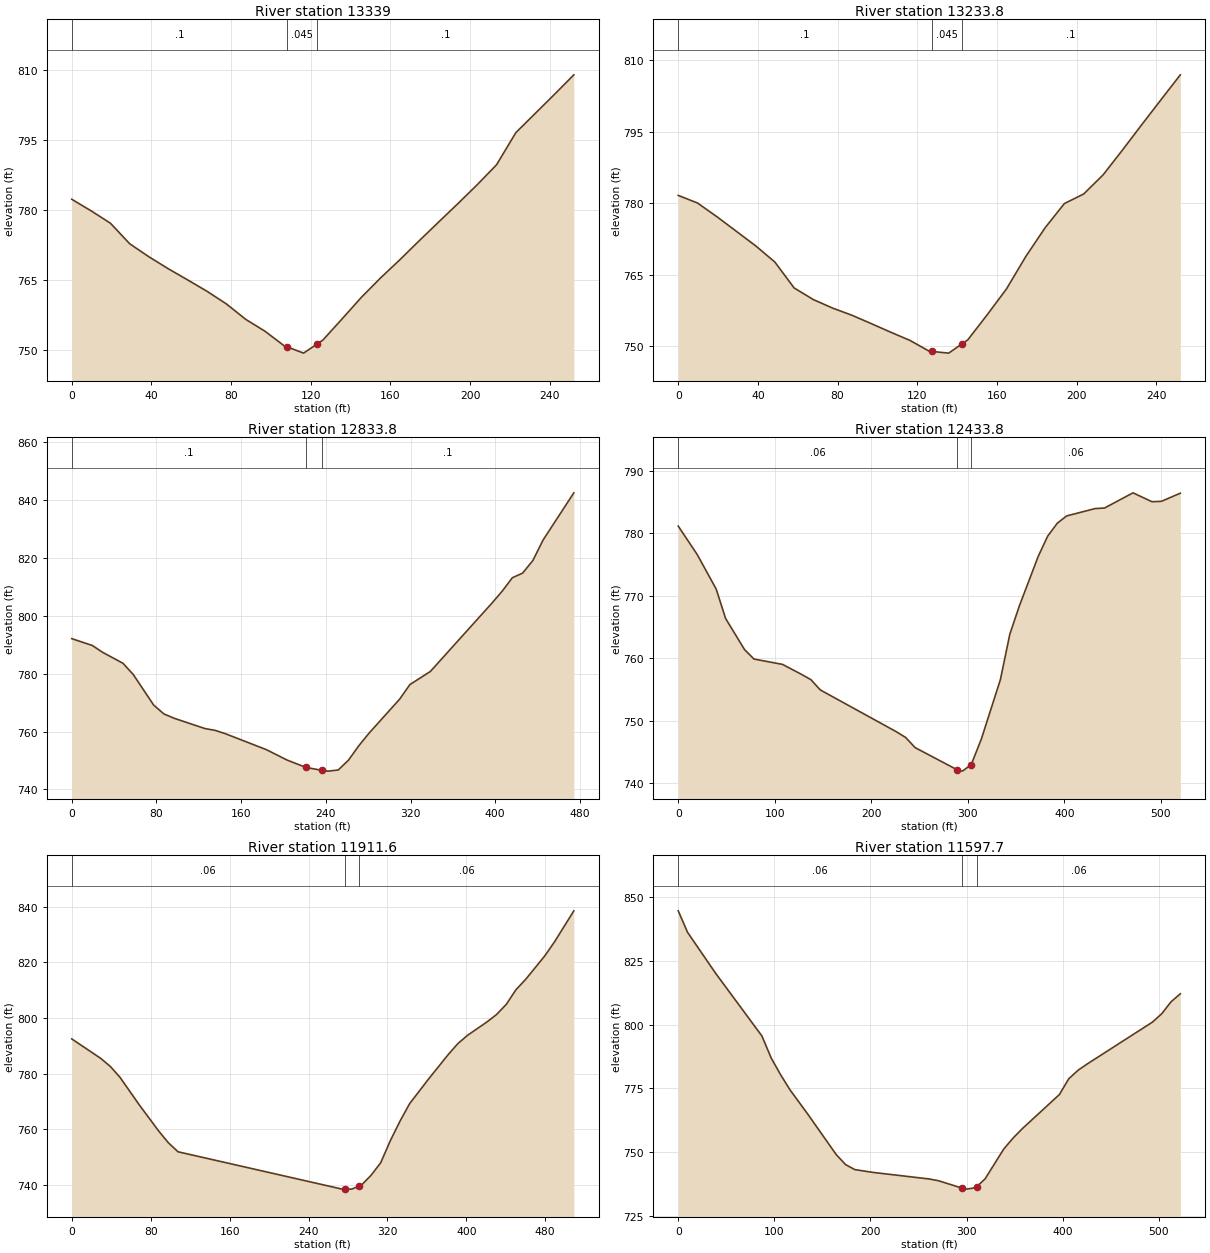
Type RM Length L Ch R = 1 ,13339   ,115.2,105.4,95.6
XS GIS Cut Line= 2
     1646363.169      347481.597     1646594.252      347380.842
#Sta/Elev= 29
       0  782.35     9.7  779.87    19.4  777.22    29.1  772.81    38.8     770
    48.5  767.45    58.2  765.06    67.9  762.63    77.6  759.93    87.3  756.62
      97  754.07   106.6  750.96   108.1  750.72   116.4  749.37   123.1   751.3
     126  752.13   135.7  756.69   145.4  761.32   155.1  765.51   164.8  769.41
   174.5  773.48   184.2  777.46   193.9  781.42   203.6  785.47   213.3  789.75
     223  796.64   232.7  800.74   242.4  804.84   252.1  809.02
#Mann= 3 , 0 , 0
       0      .1       0   108.1    .045       0   123.1      .1       0
Bank Sta=108.1,123.1
XS Rating Curve= 0 ,0
Exp/Cntr=0.3,0.1

Type RM Length L Ch R = 1 ,13233.8 ,400.8,400,399.1
XS GIS Cut Line= 2
     1646457.426      347604.351     1646625.576      347416.516
#Sta/Elev= 29
       0  781.65     9.7  780.05    19.4  777.18    29.1  774.14    38.8  771.09
    48.5  767.67    58.2  762.22    67.9  759.77    77.6  757.98    87.3  756.48
      97  754.72   106.7  752.93   116.4   751.2     126  748.95   127.5  748.89
   135.8  748.54   142.5  750.49   145.4  751.33   155.1  756.57   164.8  762.01
   174.5  768.81   184.2  774.85   193.9  779.94   203.6  781.95   213.3  785.94
     223  791.14   232.7  796.47   242.4  801.73   252.1  806.96
#Mann= 3 , 0 , 0
       0      .1       0   127.5    .045       0   142.5      .1       0
Bank Sta=127.5,142.5
XS Rating Curve= 0 ,0
Exp/Cntr=0.3,0.1

Type RM Length L Ch R = 1 ,12833.8 ,390.1,400,409.8
XS GIS Cut Line= 2
     1646676.191       347967.28     1646978.957      347602.176
#Sta/Elev= 30
       0   792.1    19.4  789.74      29   787.4    48.4  783.58    58.1   779.7
    77.4  769.14    87.1  766.07    96.8  764.58   125.8  761.03   135.5   760.4
   145.2  759.24   183.9  753.73   203.3  750.16   221.4  747.58   236.4  746.59
     242  746.32   251.7  746.71   261.4   750.1     271  755.01   280.7  759.38
   309.8  771.22   319.4  776.22   338.8  780.77   396.9  804.36   406.6  808.49
   416.2  813.14   425.9  814.74   435.6   819.1   445.3  826.21   474.3  842.48
#Mann= 3 , 0 , 0
       0      .1       0   221.4    .045       0   236.4      .1       0
Bank Sta=221.4,236.4
XS Rating Curve= 0 ,0
Exp/Cntr=0.3,0.1

Type RM Length L Ch R = 1 ,12433.8 ,501.5,521.8,542.2
XS GIS Cut Line= 2
     1646887.667      348118.753     1647355.711      347891.874
#Sta/Elev= 30
       0  781.14    19.6  776.61    39.3  771.08    49.1  766.36    68.7  761.39
    78.5  759.88     108  759.03   127.6  757.44   137.4  756.59   147.2  754.94
   225.7  748.28   235.5  747.35   245.4  745.72   288.5  742.21   294.4  741.96
   303.5     743     314  747.09   333.7  756.58   343.5  763.86   353.3  768.35
   372.9   776.3   382.7  779.53   392.6  781.59   402.4  782.77   431.8  783.94
   441.6  784.03   471.1  786.46   490.7  785.04   500.5   785.1   520.1   786.4
#Mann= 3 , 0 , 0
       0     .06       0   288.5    .045       0   303.5     .06       0
Bank Sta=288.5,303.5
XS Rating Curve= 0 ,0
Exp/Cntr=0.3,0.1

Type RM Length L Ch R = 1 ,11911.6 ,317.6,314,310.4
XS GIS Cut Line= 2
     1646862.273      348315.744     1647321.629      348535.012
#Sta/Elev= 30
       0   792.5    29.4  785.49    39.2  782.56    48.9  778.68    68.5  768.74
    88.1  759.37    97.9  755.15   107.7  751.89   274.1  738.45   276.6  738.45
   283.9  738.46   291.6  739.59   293.7   739.9   303.4  743.42   313.2  747.94
     323  755.92   332.8  762.94   342.6  769.25   362.2  778.28   381.8  786.93
   391.5  790.83   401.3  793.81   420.9   798.6   430.7  801.29   440.5  804.93
   450.3  810.18   460.1   813.9   479.6   822.4   489.4  827.41     509  838.58
#Mann= 3 , 0 , 0
       0     .06       0   276.6    .045       0   291.6     .06       0
Bank Sta=276.6,291.6
XS Rating Curve= 0 ,0
Exp/Cntr=0.3,0.1

Type RM Length L Ch R = 1 ,11597.7 ,353.1,352.6,352
XS GIS Cut Line= 2
     1646717.801      348643.064     1647218.895      348791.196
#Sta/Elev= 30
       0  844.63     9.7   836.2    38.7  820.24    87.1  795.51    96.8  786.83
   106.4  780.41   116.1   774.5   135.5  764.49   164.5  748.93   174.2  745.03
   183.8  743.08   203.2  741.96   261.3   739.4   270.9  738.71   295.5   735.8
     300  735.42   309.6  735.99   310.5  736.31   319.3  739.44   338.7  751.11
   348.4  755.43     358  759.12   396.7  772.55   406.4  778.72   416.1  782.07
   425.8  784.58   493.5  800.96   503.2  804.26   512.8  808.91   522.5  812.08
#Mann= 3 , 0 , 0
       0     .06       0   295.5    .045       0   310.5     .06       0
Bank Sta=295.5,310.5
XS Rating Curve= 0 ,0
Exp/Cntr=0.3,0.1

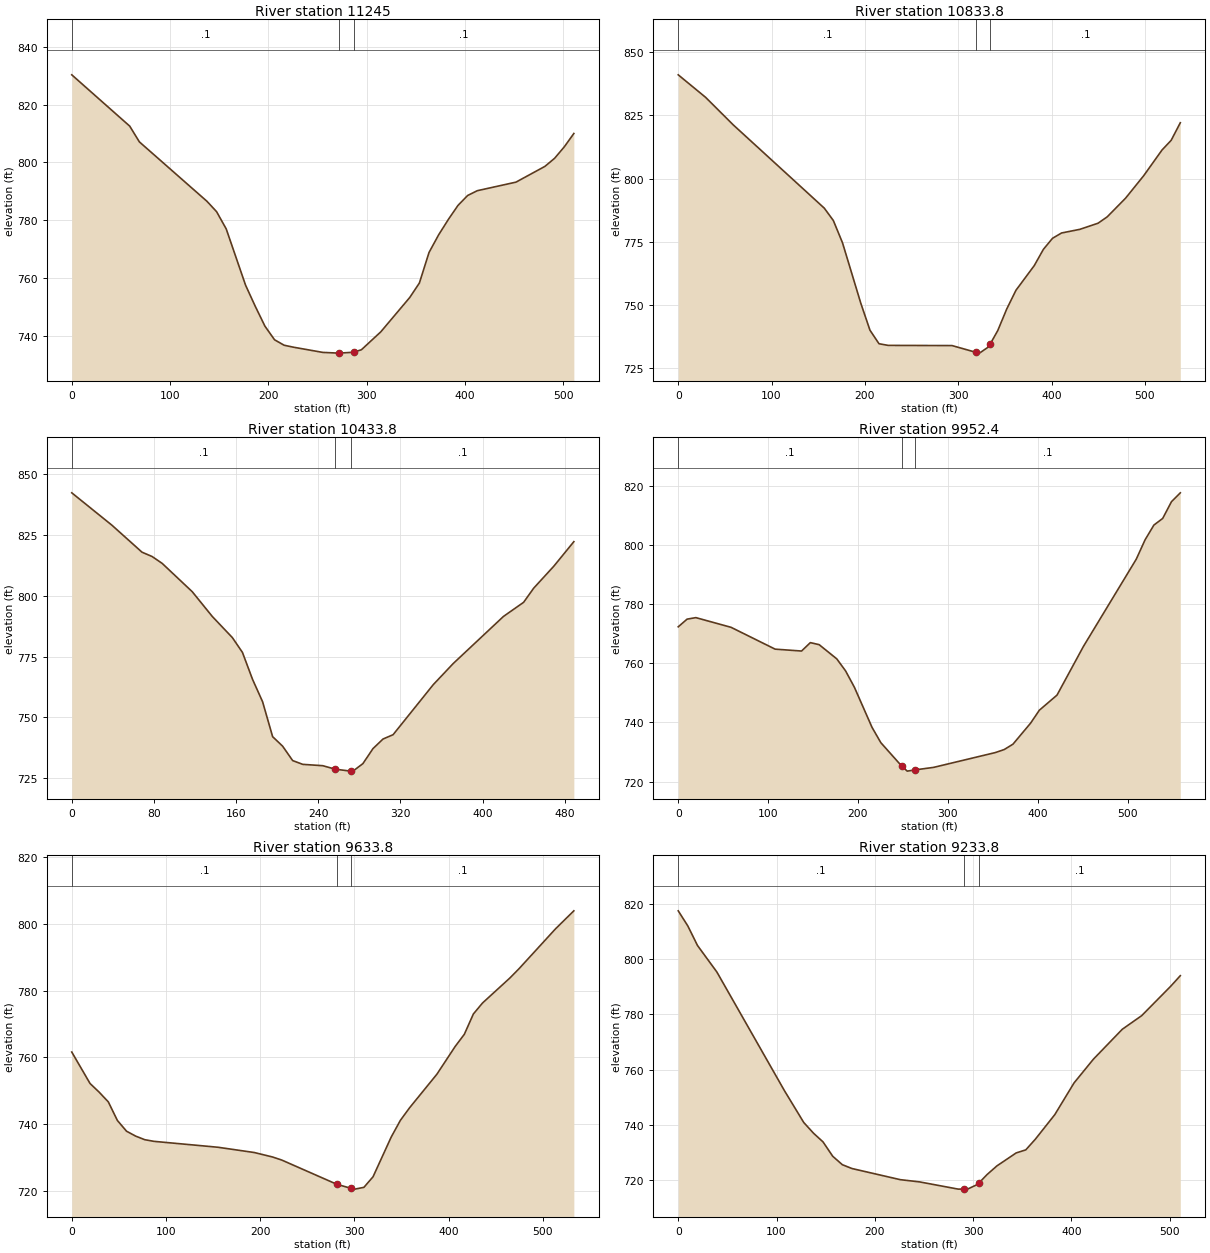
Type RM Length L Ch R = 1 ,11245   ,402.8,411,419.2
XS GIS Cut Line= 2
     1646608.864      348982.374     1647102.536      349114.451
#Sta/Elev= 30
       0  830.36      59  812.57    68.8  807.12   137.6  786.52   147.4  782.92
   157.2  776.94   176.9  757.44   186.7  750.16   196.6  743.24   206.4  738.51
   216.2  736.62     226  735.92   255.5  734.14   271.8  733.89   286.8  734.19
   294.8  735.06   314.5  741.26     344  753.18   353.8  758.19   363.6  768.77
   373.4   774.9   383.3  780.24   393.1   785.1   402.9  788.53   412.8   790.2
   452.1  793.16   481.6  798.63   491.4  801.42   501.2  805.36     511  810.02
#Mann= 3 , 0 , 0
       0      .1       0   271.8    .045       0   286.8      .1       0
Bank Sta=271.8,286.8
XS Rating Curve= 0 ,0
Exp/Cntr=0.3,0.1

Type RM Length L Ch R = 1 ,10833.8 ,395,400,405
XS GIS Cut Line= 2
     1646482.694      349248.107     1646930.332      349546.282
#Sta/Elev= 30
       0  840.98    29.3  832.09    58.7  821.28   156.5  788.27   166.2  783.38
     176  774.58   195.6   750.7   205.4  740.05   215.1  734.69   224.9  734.04
   293.4  733.96   319.3  731.26   322.7  730.98   332.5  733.45   334.3  734.63
   342.3  739.88     352  748.47   361.8  755.81   381.4  765.56   391.2  771.99
     401  776.37   410.7  778.47   430.3  779.91   449.8  782.33   459.6  784.85
   479.2   792.2   498.7  801.12   518.3  811.26   528.1  815.09   537.9  822.04
#Mann= 3 , 0 , 0
       0      .1       0   319.3    .045       0   334.3      .1       0
Bank Sta=319.3,334.3
XS Rating Curve= 0 ,0
Exp/Cntr=0.3,0.1

Type RM Length L Ch R = 1 ,10433.8 ,483.3,481,478.8
XS GIS Cut Line= 2
     1646285.781      349516.019     1646623.131      349869.833
#Sta/Elev= 30
       0  842.19    39.1   828.9    68.4  817.82    78.2  816.05      88  813.24
   117.3  801.61   136.9  791.41   156.4  782.75   166.2  776.68     176  765.65
   185.8  756.45   195.6  742.09   205.3   738.2   215.1  732.28   224.9  730.73
   244.4  730.18   256.6  728.74   271.6  727.95   273.8  727.95   283.5  731.03
   293.3  737.19   303.1  741.13   312.9  742.91     352  763.44   371.5  772.14
   420.4  791.46     440  797.25   449.8  803.05   469.3  812.02   488.9  822.14
#Mann= 3 , 0 , 0
       0      .1       0   256.6    .045       0   271.6      .1       0
Bank Sta=256.6,271.6
XS Rating Curve= 0 ,0
Exp/Cntr=0.3,0.1

Type RM Length L Ch R = 1 ,9952.4  ,319.4,318.8,318.1
XS GIS Cut Line= 2
     1645855.137      349764.092     1646277.943       350129.16
#Sta/Elev= 30
       0  772.32     9.8  774.91    19.6  775.43    58.8  772.15   107.8  764.78
   137.2  764.14     147  766.98   156.8  766.29   176.4  761.49   186.2  757.43
     196   751.9   215.6  738.36   225.4  733.18   248.6  725.27   254.8  723.56
   263.6  723.98   284.2  724.83   352.8  729.83   362.6  730.84   372.4  732.66
     392  739.76   401.8  744.15   421.4  749.24   450.8  765.69   509.6  795.18
   519.4  801.72   529.2   806.7     539  808.95   548.8  814.62   558.6   817.6
#Mann= 3 , 0 , 0
       0      .1       0   248.6    .045       0   263.6      .1       0
Bank Sta=248.6,263.6
XS Rating Curve= 0 ,0
Exp/Cntr=0.3,0.1

Type RM Length L Ch R = 1 ,9633.8  ,395.9,399.7,402.7
XS GIS Cut Line= 2
     1645746.902      350056.442     1646180.427      350366.171
#Sta/Elev= 30
       0  761.58    19.4  752.14    29.1  749.53    38.8  746.62    48.4  741.05
    58.1  737.83    67.8  736.35    77.5  735.27    87.2  734.78     155  733.01
   193.8  731.42   213.1  730.08   222.8  729.17   281.4  721.88   296.4  720.68
   300.3  720.44     310  720.97   319.7  724.14     339  736.07   348.7  741.07
   358.4  744.82   387.5  754.94   406.9  763.27   416.6  766.91   426.2  773.01
   435.9   776.3     465  783.82   474.7  786.61   513.4  798.57   532.8  803.96
#Mann= 3 , 0 , 0
       0      .1       0   281.4    .045       0   296.4      .1       0
Bank Sta=281.4,296.4
XS Rating Curve= 0 ,0
Exp/Cntr=0.3,0.1

Type RM Length L Ch R = 1 ,9233.8  ,403.8,399.9,396.1
XS GIS Cut Line= 2
     1645506.202       350189.43     1645816.439      350595.195
#Sta/Elev= 30
       0  817.38     9.8  811.89    19.6  804.85    39.3  795.27     108  752.41
   127.7  740.88   137.5  737.05   147.3  733.86   157.2  728.66     167  725.61
   176.8  724.23   225.9  720.21   245.6   719.4   284.9  716.79   290.7  716.83
   294.7  716.86   304.5  718.49   305.7  718.93   314.3  722.09   324.2  725.18
   343.8  729.87   353.6  730.98   363.4  734.87   383.1  743.71   402.7  755.18
   422.4  763.76   451.8  774.58   471.5  779.49     501   790.1   510.8  793.94
#Mann= 3 , 0 , 0
       0      .1       0   290.7    .045       0   305.7      .1       0
Bank Sta=290.7,305.7
XS Rating Curve= 0 ,0
Exp/Cntr=0.3,0.1

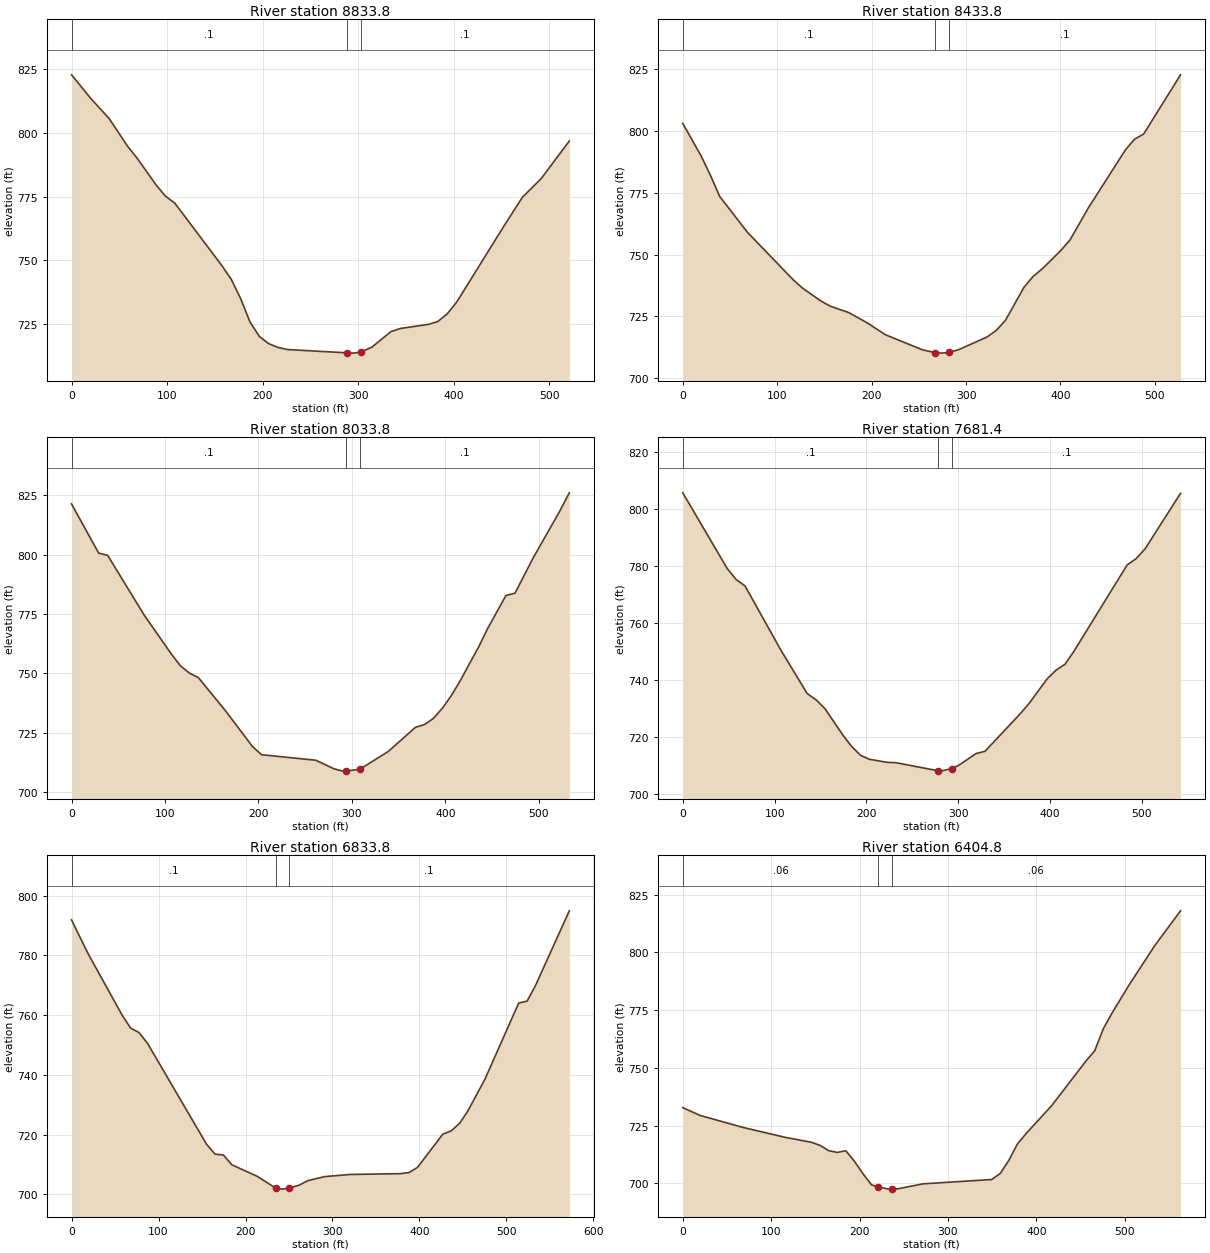
Type RM Length L Ch R = 1 ,8833.8  ,394.9,399.9,404.9
XS GIS Cut Line= 2
     1645149.881      350436.373     1645531.713      350790.706
#Sta/Elev= 30
       0  822.79    19.7  813.71    39.3  805.66      59  794.59    68.8  790.02
    88.5  779.57    98.3  775.19   108.1  772.44   157.3  747.96   167.1  742.59
   176.9  735.08   186.7  725.89   196.6  720.14   206.4  717.32   216.2  715.83
   226.1  715.02   288.1  713.74   294.8  713.62   303.1  714.06   314.5  716.02
   334.2  722.04     344  723.28   373.5   724.9   383.3  726.02   393.1  729.03
     403  733.59   452.1  763.24   471.8  774.76   491.4  782.05   520.9  796.82
#Mann= 3 , 0 , 0
       0      .1       0   288.1    .045       0   303.1      .1       0
Bank Sta=288.1,303.1
XS Rating Curve= 0 ,0
Exp/Cntr=0.3,0.1

Type RM Length L Ch R = 1 ,8433.8  ,393.1,400,407
XS GIS Cut Line= 2
     1644909.159       350667.56     1645218.258      351094.706
#Sta/Elev= 30
       0  803.15    19.5  789.92    29.3  782.12    39.1  773.58    68.4   759.1
   117.2  739.72   126.9  736.43   146.5  731.19   156.2  729.13   175.8  726.54
   195.3  722.39   214.8  717.53   253.9  711.47   267.3  710.31   273.4  710.12
   282.3  710.38   292.9  711.63   322.2  716.64     332  719.31   341.7  723.36
   361.3  736.72     371  741.15   380.8  744.29   400.3  751.63   410.1  755.92
   429.6  768.94   468.7  792.35   478.4  796.73   488.2  798.86   527.2  822.82
#Mann= 3 , 0 , 0
       0      .1       0   267.3    .045       0   282.3      .1       0
Bank Sta=267.3,282.3
XS Rating Curve= 0 ,0
Exp/Cntr=0.3,0.1

Type RM Length L Ch R = 1 ,8033.8  ,353.5,352.3,351.1
XS GIS Cut Line= 2
      1644668.21      350818.359     1644834.745      351324.238
#Sta/Elev= 30
       0  821.32      29  800.64    38.7  799.66    77.5  774.65   106.5  758.28
   116.2  753.28   125.9  750.13   135.6  748.22   164.6  734.27   193.7  719.11
   203.4  715.69   261.4  713.38   280.8  709.77   290.5  708.79   293.5  708.81
   308.5  709.57   338.9  717.07     368  727.25   377.6   728.4   387.3  731.03
     397  735.39   406.7   740.8   416.4  747.24   435.8  761.27   445.4  768.99
   464.8  782.78   474.5  783.73   493.8  798.51   522.9  818.66   532.6  826.02
#Mann= 3 , 0 , 0
       0      .1       0   293.5    .045       0   308.5      .1       0
Bank Sta=293.5,308.5
XS Rating Curve= 0 ,0
Exp/Cntr=0.3,0.1

Type RM Length L Ch R = 1 ,7681.4  ,847.9,847.5,847.2
XS GIS Cut Line= 2
     1644358.711       351011.41     1644554.312      351517.036
#Sta/Elev= 30
       0  805.53    48.4  778.97    58.1  775.14    67.8  772.87   106.5  750.54
   135.5  735.12   145.2  732.92   154.9   729.8   174.3  720.59   183.9  716.57
   193.6  713.46   203.3  712.06   222.7  710.99   232.4  710.86   278.3  708.02
   280.8  707.91   293.3  708.81   300.1  709.87   319.5  714.07   329.2  714.87
   367.9  728.18   377.6  731.84   396.9   740.3   406.6  743.34   416.3   745.4
     426  749.95     484  780.25   493.7  782.43   503.4  785.84   542.1  805.36
#Mann= 3 , 0 , 0
       0      .1       0   278.3    .045       0   293.3      .1       0
Bank Sta=278.3,293.3
XS Rating Curve= 0 ,0
Exp/Cntr=0.3,0.1

Type RM Length L Ch R = 1 ,6833.8  ,437.7,429,420.3
XS GIS Cut Line= 2
     1643715.406      351177.988     1643936.605      351705.797
#Sta/Elev= 30
       0  791.89    19.4  780.39    58.2  759.98    67.9  755.67    77.6  754.16
    87.3  750.57   155.2  716.76   164.9  713.45   174.6  713.12   184.3  709.86
   213.4     706   235.2  701.96   242.5   701.7   250.2  702.07   261.9  703.04
   271.6  704.54     291  705.89   320.1  706.61   378.3  706.89     388  707.24
   397.7  708.97   426.8   720.1   436.5  721.21   446.2  723.77   455.9  728.01
   475.3  738.53   514.1  764.05   523.8  764.71   533.5  769.96   572.3  794.96
#Mann= 3 , 0 , 0
       0      .1       0   235.2    .045       0   250.2      .1       0
Bank Sta=235.2,250.2
XS Rating Curve= 0 ,0
Exp/Cntr=0.3,0.1

Type RM Length L Ch R = 1 ,6404.8  ,435.4,421.9,408.5
XS GIS Cut Line= 2
     1643249.041       351383.66     1643645.641      351783.517
#Sta/Elev= 30
       0  732.77    19.4  729.42      68   724.2   116.5  719.84   145.6  717.76
   155.4   716.4   165.1  714.14   174.8  713.37   184.5  714.09   194.2  709.54
   203.9  704.12   213.6  699.31   221.2  698.43     233  697.46   236.2   697.5
   242.8  697.57   271.9  699.75   349.6  701.62   359.3   704.3     369  709.97
   378.7  717.05   388.4   721.5   417.5  733.68   456.4  753.07   466.1  757.38
   475.8  766.92   485.5  773.61   504.9  785.85     534  802.95   563.2  818.04
#Mann= 3 , 0 , 0
       0     .06       0   221.2    .045       0   236.2     .06       0
Bank Sta=221.2,236.2
XS Rating Curve= 0 ,0
Exp/Cntr=0.3,0.1

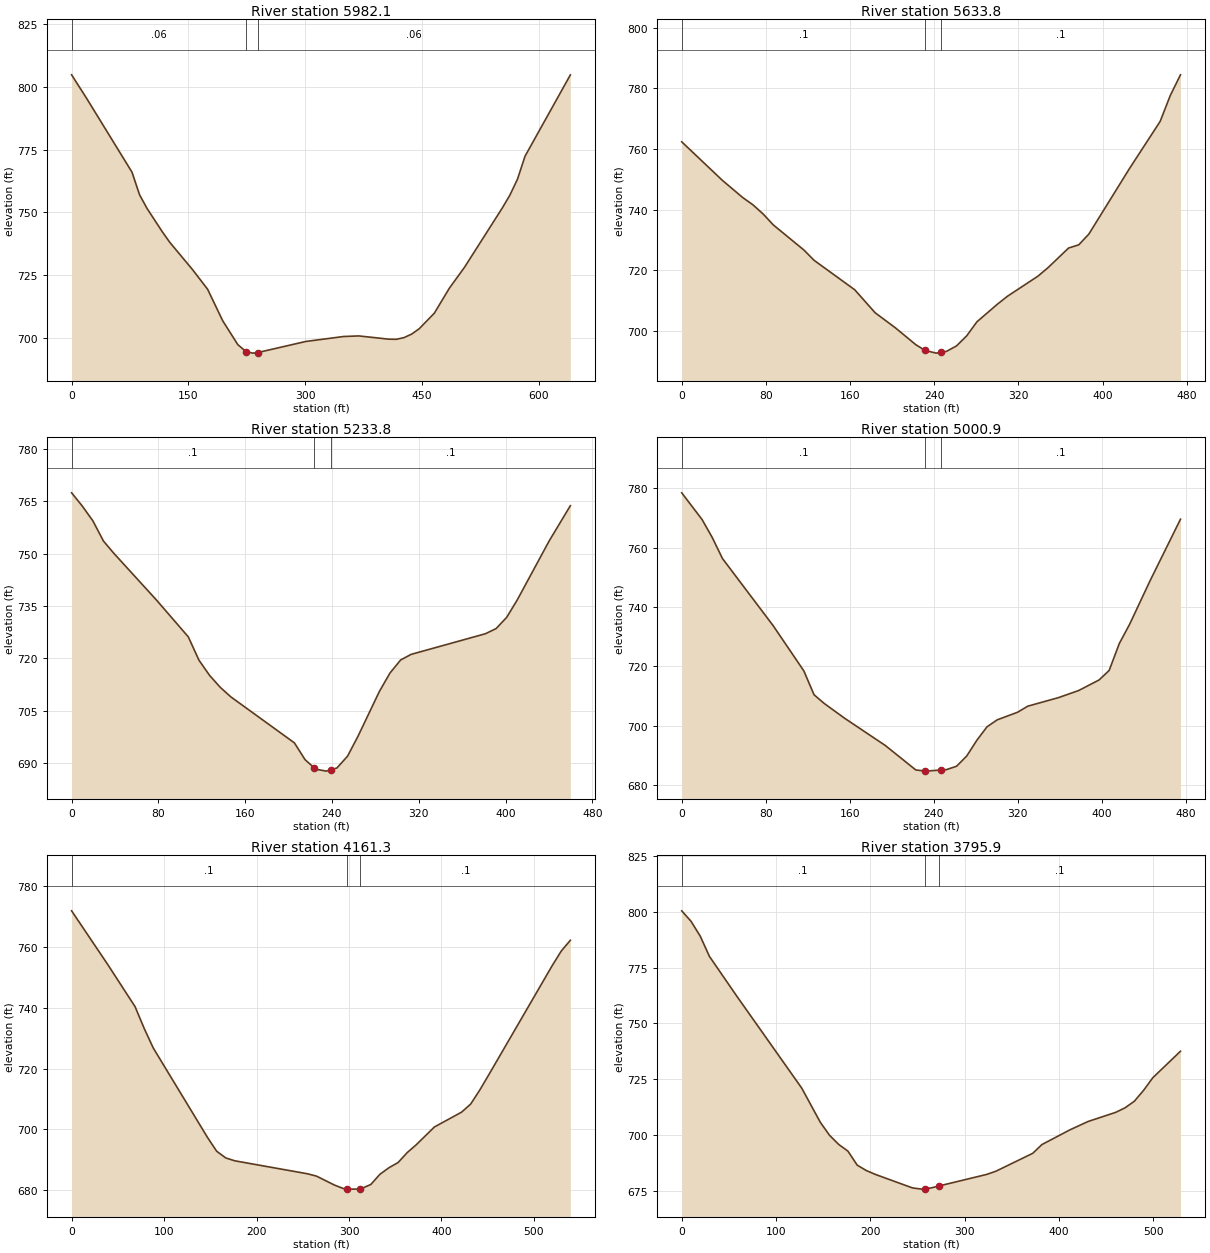
Type RM Length L Ch R = 1 ,5982.1  ,349.5,348.8,348
XS GIS Cut Line= 2
     1642946.814      351790.881     1643575.516      351913.157
#Sta/Elev= 30
       0  804.79    19.4  795.36    77.6  765.96    87.3  756.95      97  751.47
   116.4  742.26   126.2  737.97   155.3  727.14   174.7   719.3   194.1  706.72
   213.5  697.22   224.2   694.4   232.9  693.85   239.2  694.09   300.8   698.5
   349.4  700.48   368.8  700.71   407.6   699.4   417.3  699.37     427  700.05
   436.7  701.44   446.4  703.57   465.8  709.77   485.2  719.77   504.6  728.09
   553.1  751.72   562.8  756.81   572.6   763.2   582.3  772.36   640.5  804.77
#Mann= 3 , 0 , 0
       0     .06       0   224.2    .045       0   239.2     .06       0
Bank Sta=224.2,239.2
XS Rating Curve= 0 ,0
Exp/Cntr=0.3,0.1

Type RM Length L Ch R = 1 ,5633.8  ,402.2,399.9,397.6
XS GIS Cut Line= 2
     1642995.822      352127.971     1643463.458      352206.042
#Sta/Elev= 30
       0  762.37    38.7  749.67      58  744.02    67.7  741.63    77.4  738.61
    87.1     735   116.1  726.76   125.8  723.36   164.5  713.65   183.8   706.1
   203.2   701.1   222.5  695.57   231.3  693.68   241.9  692.79   246.3  693.04
   251.6  693.35   261.2  695.17   270.9  698.48   280.6   703.1     300  708.88
   309.6  711.51   338.6  718.13   348.3  720.96   367.7  727.39   377.4  728.45
     387  731.98   425.7  753.61   454.8   769.1   464.4  777.62   474.1  784.43
#Mann= 3 , 0 , 0
       0      .1       0   231.3    .045       0   246.3      .1       0
Bank Sta=231.3,246.3
XS Rating Curve= 0 ,0
Exp/Cntr=0.3,0.1

Type RM Length L Ch R = 1 ,5233.8  ,230,232.8,235.6
XS GIS Cut Line= 2
      1642915.23      352515.393     1643374.019      352545.619
#Sta/Elev= 30
       0  767.37     9.8  763.61    19.6  759.36    29.4  753.57    39.1  750.02
    78.3  736.69   107.6  726.17   117.4  719.52   127.2  715.16     137  711.76
   146.7  709.04   205.4  695.86   215.2  691.07   223.9  688.65     225  688.34
   234.8  687.78   238.9  688.16   244.6  688.68   254.4  692.06   264.1   697.8
   283.7  710.54   293.5  715.83   303.3  719.56     313  721.17   381.5  727.07
   391.3  728.54   401.1  731.76   410.9  736.77   440.2  753.58   459.8  763.69
#Mann= 3 , 0 , 0
       0      .1       0   223.9    .045       0   238.9      .1       0
Bank Sta=223.9,238.9
XS Rating Curve= 0 ,0
Exp/Cntr=0.3,0.1

Type RM Length L Ch R = 1 ,5000.9  ,831.3,839.4,847.4
XS GIS Cut Line= 2
     1642841.925      352704.127     1643308.085      352794.712
#Sta/Elev= 30
       0  778.47    19.4  769.47    29.1   763.4    38.8  756.34    87.2  733.65
   116.3  718.47     126  710.43   135.7   707.5   155.1  702.52   193.8  693.35
   222.9  685.09     232  684.72   232.6   684.7     247  685.08     252   685.2
   261.7  686.34   271.4   689.8     281  695.09   290.7  699.63   300.4  701.98
   319.8  704.54   329.5  706.58   358.6  709.45     378  711.86   397.4  715.42
     407  718.62   416.7  727.73   426.4  734.12   445.8  748.74   474.9  769.58
#Mann= 3 , 0 , 0
       0      .1       0     232    .045       0     247      .1       0
Bank Sta=232,247
XS Rating Curve= 0 ,0
Exp/Cntr=0.3,0.1

Type RM Length L Ch R = 1 ,4161.3  ,365.7,365.4,365.2
XS GIS Cut Line= 2
     1642706.345      353383.877     1643172.191      353655.784
#Sta/Elev= 30
       0  771.95    39.2  754.21    68.6   740.4    78.5  733.21    88.3  726.77
   147.1  697.24   156.9  692.75   166.7  690.55   176.5   689.6     255  685.33
   264.8  684.56   284.4  681.59   294.2  680.43   297.3  680.38     304  680.27
   312.3  680.31   323.6   681.8   333.4  685.15   343.2  687.32   353.1  689.03
   362.9  692.29   372.7  694.88   392.3  700.73   421.7  705.62   431.5  708.26
   441.3  712.84   451.1   717.9   519.8  753.92   529.6  758.72   539.4  762.25
#Mann= 3 , 0 , 0
       0      .1       0   297.3    .045       0   312.3      .1       0
Bank Sta=297.3,312.3
XS Rating Curve= 0 ,0
Exp/Cntr=0.3,0.1

Type RM Length L Ch R = 1 ,3795.9  ,220.7,227.1,233.4
XS GIS Cut Line= 2
       1642507.2      353678.139     1642963.966      353944.746
#Sta/Elev= 30
       0  800.44     9.8  795.79    19.6  789.13    29.4  780.02    58.8  761.96
   127.3  720.97   146.9  705.72   156.7  699.86   166.5  695.74   176.3  692.72
   186.1  686.46   195.9  684.01   205.7  682.25   244.8  676.24   254.6  675.71
   257.7  675.88   264.4  676.24   272.7  677.11   323.2  682.28     333   683.7
   372.2  691.75     382  695.69   411.4  702.22   430.9  706.02   460.3  710.13
   470.1  712.15   479.9  715.07   489.7  719.93   499.5  725.61   528.9  737.51
#Mann= 3 , 0 , 0
       0      .1       0   257.7    .045       0   272.7      .1       0
Bank Sta=257.7,272.7
XS Rating Curve= 0 ,0
Exp/Cntr=0.3,0.1