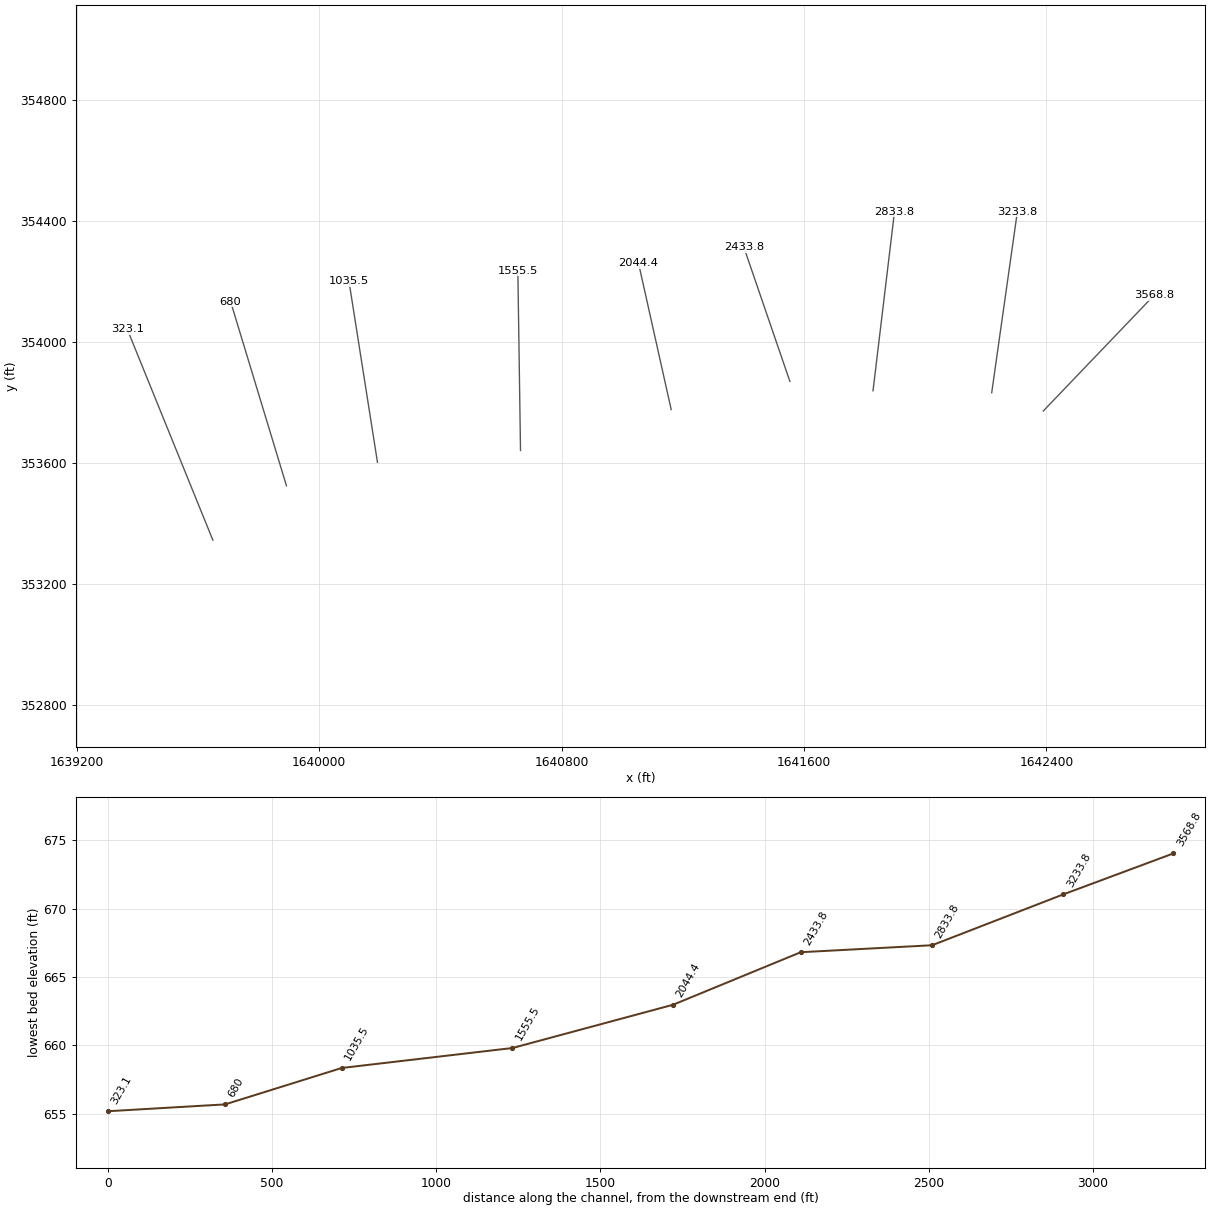
HEC-RAS study BUCKFRK.prj: BUCKFRK

--- BUCKFRK.g01 (geometry) --- (continued)

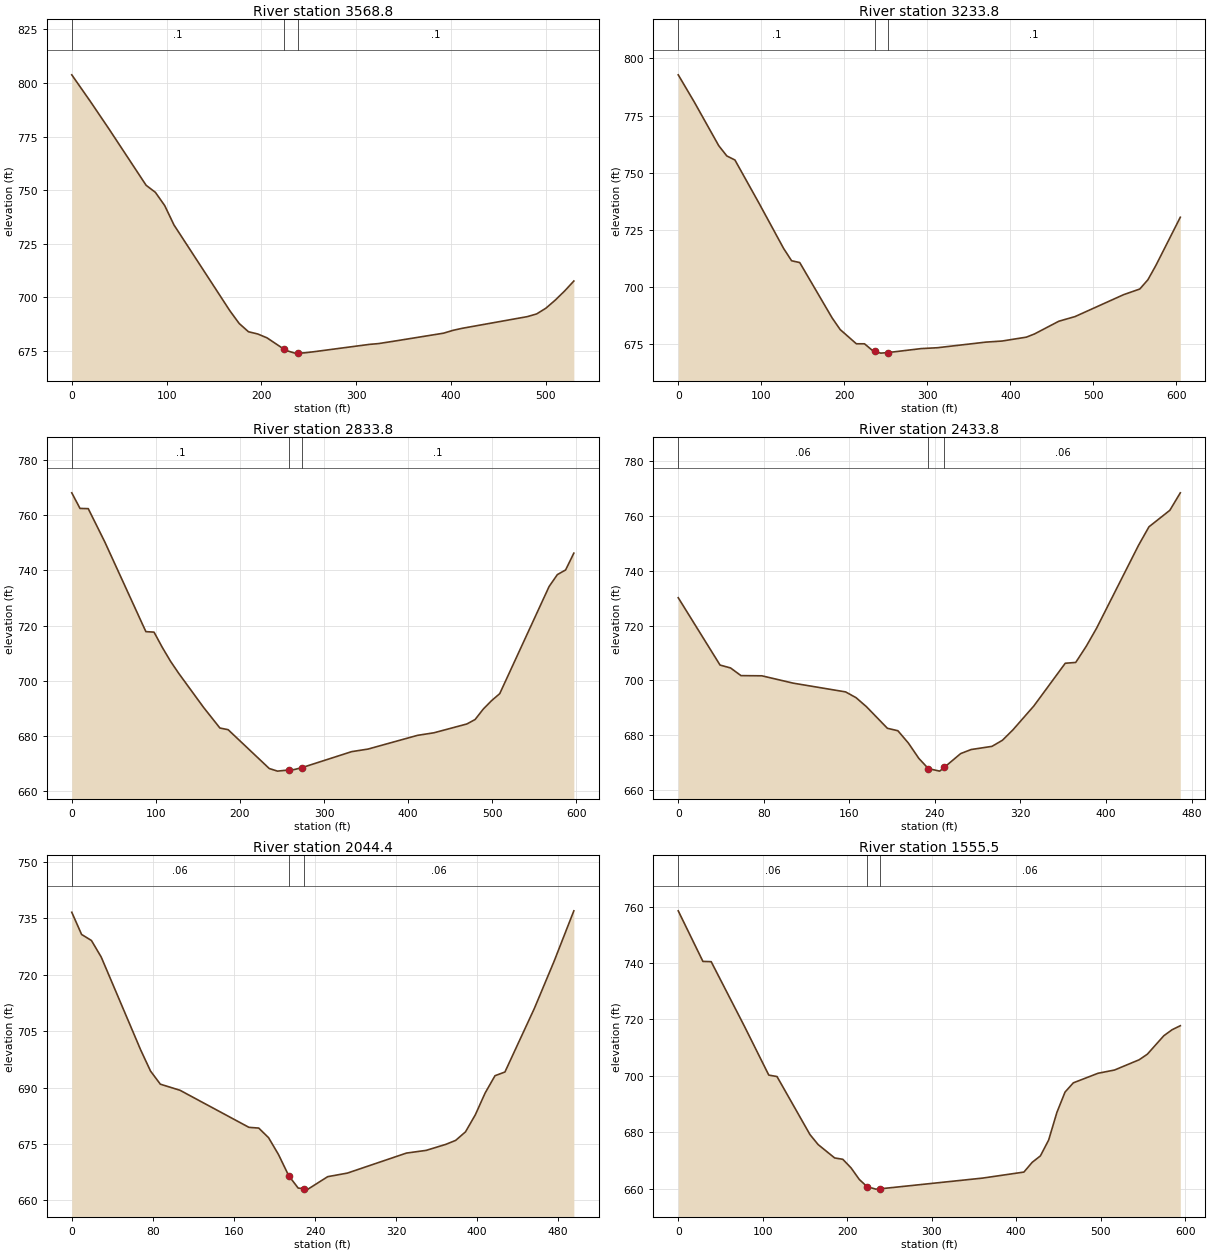
Type RM Length L Ch R = 1 ,3568.8  ,320.8,334.9,349
XS GIS Cut Line= 2
     1642389.497      353771.549     1642755.192      354154.323
#Sta/Elev= 30
       0  803.85    19.6  791.44    39.2  778.63    78.4  752.32    88.2  749.02
      98  742.85   107.8   733.8   166.7   693.8   176.5  687.87   186.3  684.01
   196.1  682.96   205.9  681.15   223.6  675.91   225.5  675.34   235.3  674.03
   238.6  674.07   245.1  674.15   254.9  674.66   313.7   678.1   323.5  678.48
   343.1  679.84   392.1  683.34   401.9  684.65   411.7  685.61   480.4  691.06
   490.2  692.32     500  695.01   509.8  698.76   519.6  702.98   529.4  707.66
#Mann= 3 , 0 , 0
       0      .1       0   223.6    .045       0   238.6      .1       0
Bank Sta=223.6,238.6
XS Rating Curve= 0 ,0
Exp/Cntr=0.3,0.1

Type RM Length L Ch R = 1 ,3233.8  ,399.5,400,400.4
XS GIS Cut Line= 2
     1642219.349      353831.936     1642304.004      354430.553
#Sta/Elev= 30
       0  792.84    19.5  780.83    48.8  761.82    58.5  757.34    68.3  755.55
    97.5  736.51   126.8  716.92   136.5  711.47   146.3  710.68   185.3  686.46
     195  681.36   214.5  675.13   224.3  675.12     234  672.18   237.1  671.82
   243.8  671.04   252.1  671.26   292.5  673.02     312   673.4   370.5  675.86
     390  676.33   419.3  678.04     429  679.43   458.3     685   477.8  687.03
   536.3  696.62   555.8   699.1   565.6  703.16   575.3   709.5   604.6  730.51
#Mann= 3 , 0 , 0
       0      .1       0   237.1    .045       0   252.1      .1       0
Bank Sta=237.1,252.1
XS Rating Curve= 0 ,0
Exp/Cntr=0.3,0.1

Type RM Length L Ch R = 1 ,2833.8  ,389.9,400,410.1
XS GIS Cut Line= 2
     1641827.639      353838.487     1641898.631      354431.145
#Sta/Elev= 30
       0  768.07     9.8  762.42    19.6  762.34    39.1   750.4    88.1  717.82
    97.8  717.64   107.6  712.13   117.4   707.1   127.2   702.7   156.6  690.43
   176.1  682.93   185.9  682.32   234.8  668.26   244.6  667.32   258.8  667.77
   264.2  667.87   273.8   668.6   332.7  674.37   352.3  675.31     411  680.27
   430.6   681.2   469.7  684.39   479.5     686   489.3  689.81     499  692.81
   508.8  695.37   567.5  734.16   577.3  738.46   587.1  740.14   596.9  746.24
#Mann= 3 , 0 , 0
       0      .1       0   258.8    .045       0   273.8      .1       0
Bank Sta=258.8,273.8
XS Rating Curve= 0 ,0
Exp/Cntr=0.3,0.1

Type RM Length L Ch R = 1 ,2433.8  ,391.4,389,386.7
XS GIS Cut Line= 2
     1641553.225      353869.708     1641401.119      354313.884
#Sta/Elev= 30
       0  730.18    39.1  705.57    48.9  704.52    58.7  701.71    78.2  701.64
   107.6  698.95   156.5  695.76   166.3  693.65   176.1  690.32   195.6  682.46
   205.4  681.57   215.2  677.08     225  671.46   233.9  667.73   244.5  666.81
   248.9  668.22   264.1  673.22   273.9   674.7   293.4  675.86   303.2   678.1
     313   681.9   332.6  690.65   361.9  706.23   371.7  706.53   381.5  712.41
   391.2  719.04   430.4  749.31   440.2   756.1   459.7  762.12   469.5  768.51
#Mann= 3 , 0 , 0
       0     .06       0   233.9    .045       0   248.9     .06       0
Bank Sta=233.9,248.9
XS Rating Curve= 0 ,0
Exp/Cntr=0.3,0.1

Type RM Length L Ch R = 1 ,2044.4  ,494.1,488.9,483.8
XS GIS Cut Line= 2
      1641161.54      353776.522     1641053.805      354260.009
#Sta/Elev= 30
       0  736.63     9.7  730.72    19.4  729.12    29.1  724.69      68     700
    77.7  694.39    87.4  690.89   106.8  689.27   174.8  679.41   184.5  679.21
   194.2  676.65     204  672.16   214.1  666.53   223.4  663.25   229.1  663.09
   233.1  662.97   252.5  666.28     272  667.24   330.2  672.56   349.7  673.28
   369.1  674.88   378.8  675.94   388.5  678.21   398.2  682.75   407.9  688.56
   417.6  693.14   427.4  694.13   456.5  711.08   475.9  723.58   495.4  737.01
#Mann= 3 , 0 , 0
       0     .06       0   214.1    .045       0   229.1     .06       0
Bank Sta=214.1,229.1
XS Rating Curve= 0 ,0
Exp/Cntr=0.3,0.1

Type RM Length L Ch R = 1 ,1555.5  ,516.4,520,523.6
XS GIS Cut Line= 2
     1640664.279      353641.182     1640655.513      354235.334
#Sta/Elev= 30
       0  758.54    29.2   740.6      39   740.5    77.9  717.84   107.2  700.26
   116.9  699.75   155.9  679.17   165.6  675.61   185.1  670.88   194.8  670.39
   204.6  667.32   214.3  663.24   223.4  660.71   233.8  659.81   238.4   659.9
   360.4  663.73   409.1  665.86   418.9  669.32   428.6  671.59   438.4  677.24
   448.1  686.99   457.8  694.25   467.6  697.52   496.8  700.91   516.3  702.06
   545.5   705.7   555.2  707.68   574.7  714.23   584.5  716.36   594.2  717.78
#Mann= 3 , 0 , 0
       0     .06       0   223.4    .045       0   238.4     .06       0
Bank Sta=223.4,238.4
XS Rating Curve= 0 ,0
Exp/Cntr=0.3,0.1

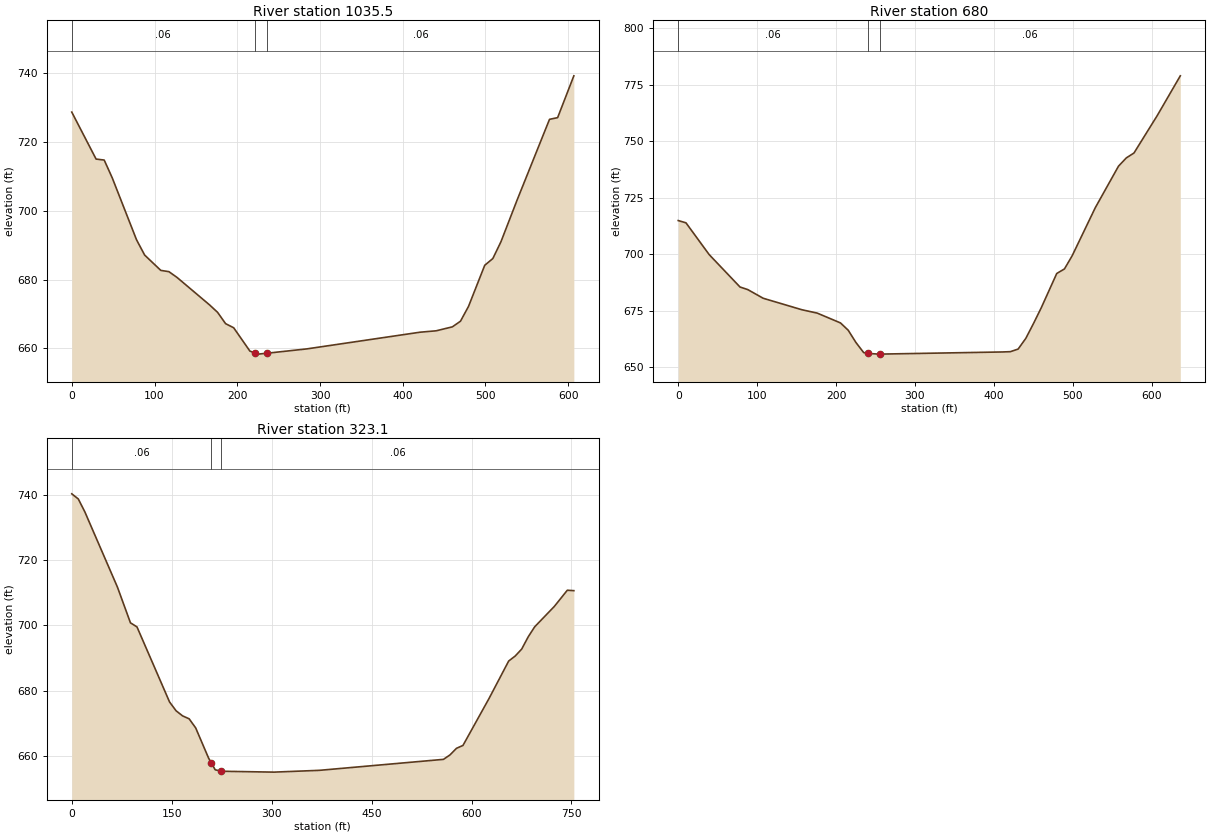
Type RM Length L Ch R = 1 ,1035.5  ,352.4,355.3,358.2
XS GIS Cut Line= 2
     1640192.193      353601.946     1640098.025      354201.352
#Sta/Elev= 30
       0  728.61    29.4  714.97    39.2  714.69    48.9  709.53    78.3  691.53
    88.1   687.1   107.6  682.66   117.4  682.29   127.2  680.62   166.4  672.67
   176.2  670.49   185.9   667.2   195.7     666   215.3  659.23   221.2   658.7
   225.1  658.35   236.2  658.62   283.8  659.86   420.8  664.71   440.4  665.12
     460  666.27   469.8  667.91   479.5   672.2   499.1  684.14   508.9   686.1
   518.7  690.97   538.2  703.06   577.4  726.51   587.2     727   606.8  739.14
#Mann= 3 , 0 , 0
       0     .06       0   221.2    .045       0   236.2     .06       0
Bank Sta=221.2,236.2
XS Rating Curve= 0 ,0
Exp/Cntr=0.3,0.1

Type RM Length L Ch R = 1 ,680     ,355.3,357.1,358.8
XS GIS Cut Line= 2
      1639891.81      353524.401     1639707.478      354133.449
#Sta/Elev= 30
       0  714.88     9.8  713.87    39.2   699.8    78.3  685.43    88.1  684.29
   107.7  680.44   156.6  675.37   176.2  673.86   205.6  669.52   215.4  666.29
   225.2  660.85     235  656.38   240.7  655.99   254.5  655.69   255.7   655.7
   411.2  656.65     421  656.78   430.8  657.94   440.5  662.68   450.3  669.29
   460.1  676.25   479.7  691.42   489.5  693.45   499.3  699.31   528.6  720.61
     558  738.99   567.8  742.62   577.6  744.82     607  761.36   636.3  779.01
#Mann= 3 , 0 , 0
       0     .06       0   240.7    .045       0   255.7     .06       0
Bank Sta=240.7,255.7
XS Rating Curve= 0 ,0
Exp/Cntr=0.3,0.1

Type RM Length L Ch R = 1 ,323.1   ,323.1,323.1,323
XS GIS Cut Line= 2
     1639648.976      353344.524      1639366.04      354043.022
#Sta/Elev= 30
       0  740.23     9.8  738.66    19.6  734.73    68.5  711.75    88.1  700.81
    97.9  699.56   146.8  676.62   156.6  673.93   166.4  672.37   176.2  671.48
     186   668.7   205.5  659.42   209.6  657.95   215.3   655.9   224.6  655.46
   303.4  655.19   371.9  655.74   557.9  659.09   567.7  660.45   577.4  662.46
   587.2  663.35   626.4  677.73   655.8  689.14   665.5  690.65   675.3  692.78
   685.1  696.53   694.9  699.61   724.3  705.82   743.8  710.77   753.6  710.64
#Mann= 3 , 0 , 0
       0     .06       0   209.6    .045       0   224.6     .06       0
Bank Sta=209.6,224.6
XS Rating Curve= 0 ,0
Exp/Cntr=0.3,0.1

Chan Stop Cuts=-1
Use User Specified Reach Order=0
Composite Channel Slope=5